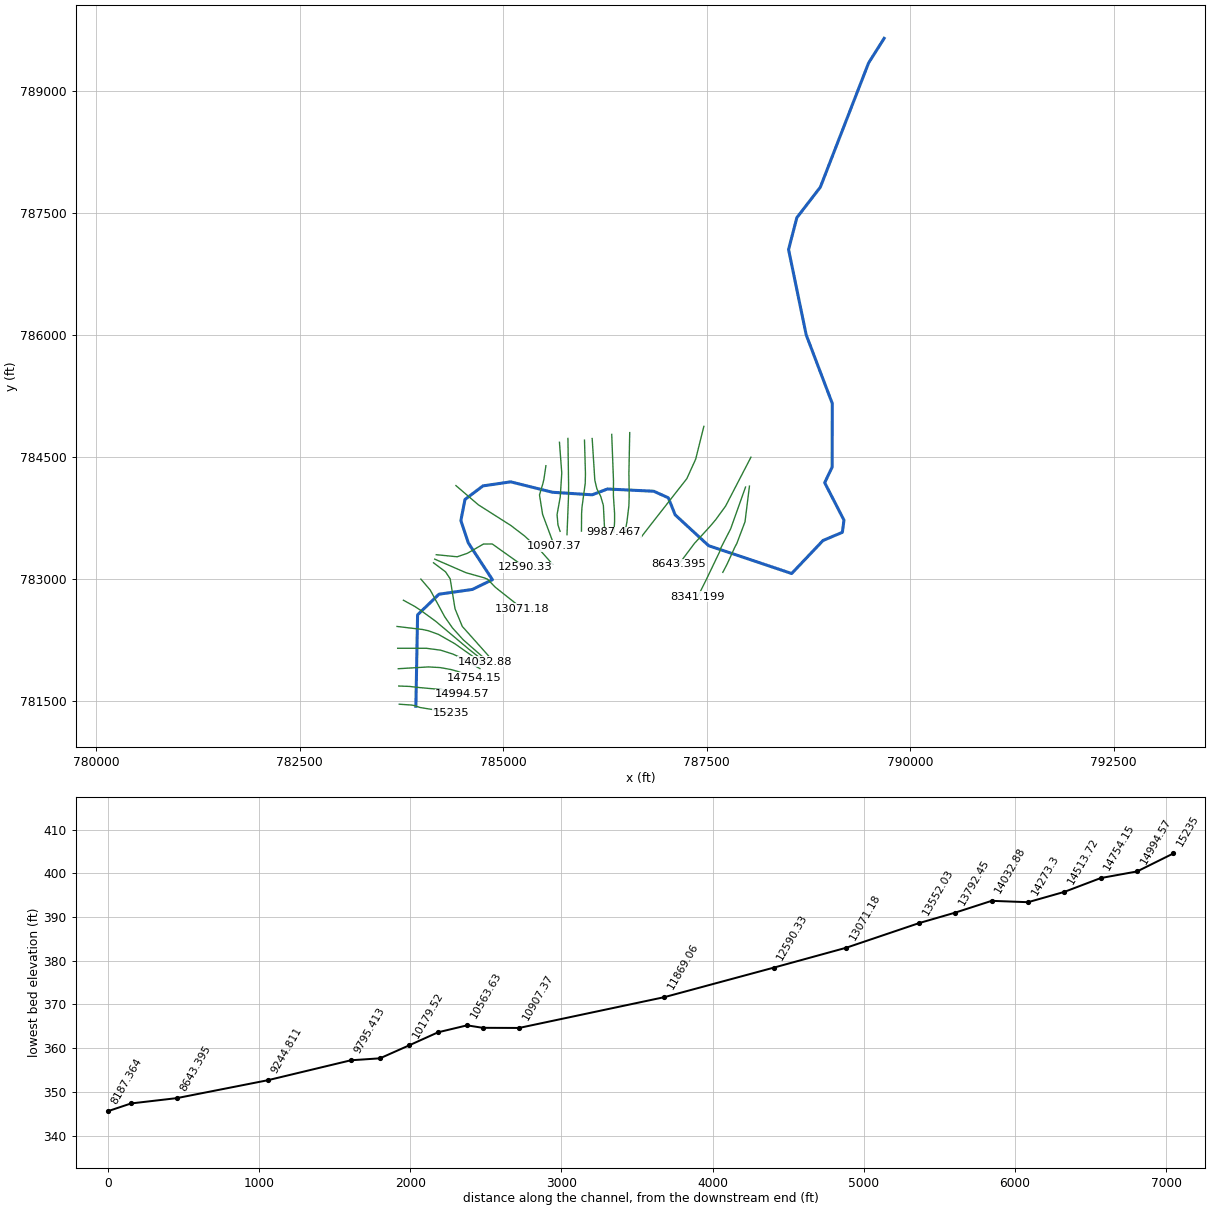
--- 17521_ras.prj (project) ---

Proj Title=17521
Current Plan=p01
Default Exp/Contr=0.3,0.1
English Units
Geom File=g01
Flow File=f01
Plan File=p01
Y Axis Title=Elevation
X Axis Title(PF)=Main Channel Distance
X Axis Title(XS)=Station
BEGIN DESCRIPTION:
RFD model 17521 exported to HEC-RAS
END DESCRIPTION:

--- 17521_ras.p01 (plan) ---

Plan Title=Plan 01
Program Version=4.10
Short Identifier=Plan 01
Geom File=g01
Flow File=f01
Subcritical Flow
Calc Critical at every XS
Secant Critical Depth

--- 17521_ras.f01 (steady flow) ---

Flow Title=Flow 01
Program Version=5.01
Number of Profiles= 6
Profile Names=10yr,25yr,50yr,100yr,100plus,500yr
River Rch & RM=17521,36,   15235
 2660.29 4526.57 6376.64 8165.5511921.7114834.67
River Rch & RM=17521,36,14994.57
 2662.98 4531.25 6383.35 8174.2511934.4114848.68
River Rch & RM=17521,36,14754.15
 2668.33  4540.6 6396.73 8191.6311959.78 14876.7
River Rch & RM=17521,36,14513.72
 2677.96 4557.34 6420.68 8222.67 12005.114926.55
River Rch & RM=17521,36, 14273.3
 2724.48 4638.35  6536.6    837312224.5815167.89
River Rch & RM=17521,36,14032.88
 2726.15 4641.26 6540.77  8378.412232.4715176.58
River Rch & RM=17521,36,13792.45
 2746.67 4677.11 6592.17 8445.1912329.98 15284.1
River Rch & RM=17521,36,13552.03
 2747.82 4679.12 6595.07 8448.9612335.4815290.16
River Rch & RM=17521,36,13071.18
 2785.07 4744.32 6688.65 8570.6612513.1715486.21
River Rch & RM=17521,36,12590.33
 2787.97 4749.41 6695.99 8580.2312527.1415501.71
River Rch & RM=17521,36,11869.06
 2889.22 4926.57 6950.28 8910.89 13009.916032.08
River Rch & RM=17521,36,10907.37
 2920.19 4980.94  7028.5 9012.8113158.7116195.77
River Rch & RM=17521,36,10666.94
 2923.06 4985.98 7035.76 9022.2813172.53   16211
River Rch & RM=17521,36,10563.63
 2923.38 4986.55 7036.57 9023.3313174.0716212.69
River Rch & RM=17521,36,10371.58
 2926.74 4992.46 7045.07 9034.4113190.2416230.46
River Rch & RM=17521,36,10179.52
 2937.33 5011.04 7071.79 9069.2213241.0616286.24
River Rch & RM=17521,36,9987.467
 2951.19 5035.24  7106.5  9114.313306.8816357.97
River Rch & RM=17521,36,9795.413
 2952.85 5038.12 7110.62 9119.6413314.67 16366.4
River Rch & RM=17521,36,9244.811
 2973.83 5074.55 7162.64 9186.9813412.9916472.48
River Rch & RM=17521,36,8643.395
 2980.79 5086.63 7179.92 9209.3613445.6716507.78
River Rch & RM=17521,36,8341.199
 2983.95 5092.12 7187.75  9219.513460.4716523.74
River Rch & RM=17521,36,8187.364
 2988.81 5100.54 7199.76 9235.0313483.1416548.09
River Rch & RM=17521,36, 8099.18
 2990.02 5102.62 7202.71 9238.8213488.6816553.96
River Rch & RM=17521,36,7860.544
 2995.07 5111.35 7215.15  9254.913512.1516579.13
River Rch & RM=17521,36,7383.272
 3346.88 5715.05 8071.1710355.6115119.1918267.08
River Rch & RM=17521,36,6905.999
 3348.74 5718.25 8075.7110361.4415127.7118275.96
River Rch & RM=17521,36,6667.363
 3360.35 5738.13 8103.8710397.6215180.5318330.82
River Rch & RM=17521,36, 6190.09
 3365.66 5747.14 8116.5510413.8115204.17   18355
River Rch & RM=17521,36,5951.454
 3386.22 5782.46 8166.6910478.3315298.3618453.21
River Rch & RM=17521,36,5712.818
 3388.09 5785.68 8171.2410484.1715306.8918462.06
River Rch & RM=17521,36,5474.181
 3397.67 5802.06 8194.4310513.9415350.3518507.06
River Rch & RM=17521,36,5235.545
 3398.18 5802.94 8195.6710515.5315352.6818509.47
Boundary for River Rch & Prof#=17521,36,1
Up Type= 0
Dn Type= 2
Boundary for River Rch & Prof#=17521,36,2
Up Type= 0
Dn Type= 2
Boundary for River Rch & Prof#=17521,36,2
Up Type= 0
Dn Type= 2
Boundary for River Rch & Prof#=17521,36,2
Up Type= 0
Dn Type= 2
Boundary for River Rch & Prof#=17521,36,2
Up Type= 0
Dn Type= 2
Boundary for River Rch & Prof#=17521,36,2
Up Type= 0
Dn Type= 2

--- 17521_ras.g01 (geometry) ---

Geom Title=17521
Program Version=4.10

River Reach=17521,36
Reach XY= 30
783928.729463338781437.536605827783949.641032698782561.929068249
784212.635997832782814.948867805784622.292236924782873.713023102
784868.864868163782993.411966557784573.729230554783443.519529438
784481.054564833783719.907169557784531.854822428783979.847758853
 784753.03754282784146.285763296785093.188995841 784196.06546737
785606.494406879784067.933614358786093.407763216784036.649502734
786281.273565473784108.026930401786849.936919479784080.531140432
787029.422157437784000.105848712787113.207096013783790.564498624
787523.927066893783411.516055965788544.233220103783069.289145596
 788928.99105853783474.903295014789167.074904175783575.843974392
789186.594331176783725.539145598 788949.61516452784185.608590011
789041.629053444784377.448867792789042.496348531785160.963829949
788722.678688466 786002.40023724788506.085172238787051.451351855
788607.709349574787442.788574137 788896.44422722787818.298906945
789489.006598562789344.667236549789680.011457862789647.015918818

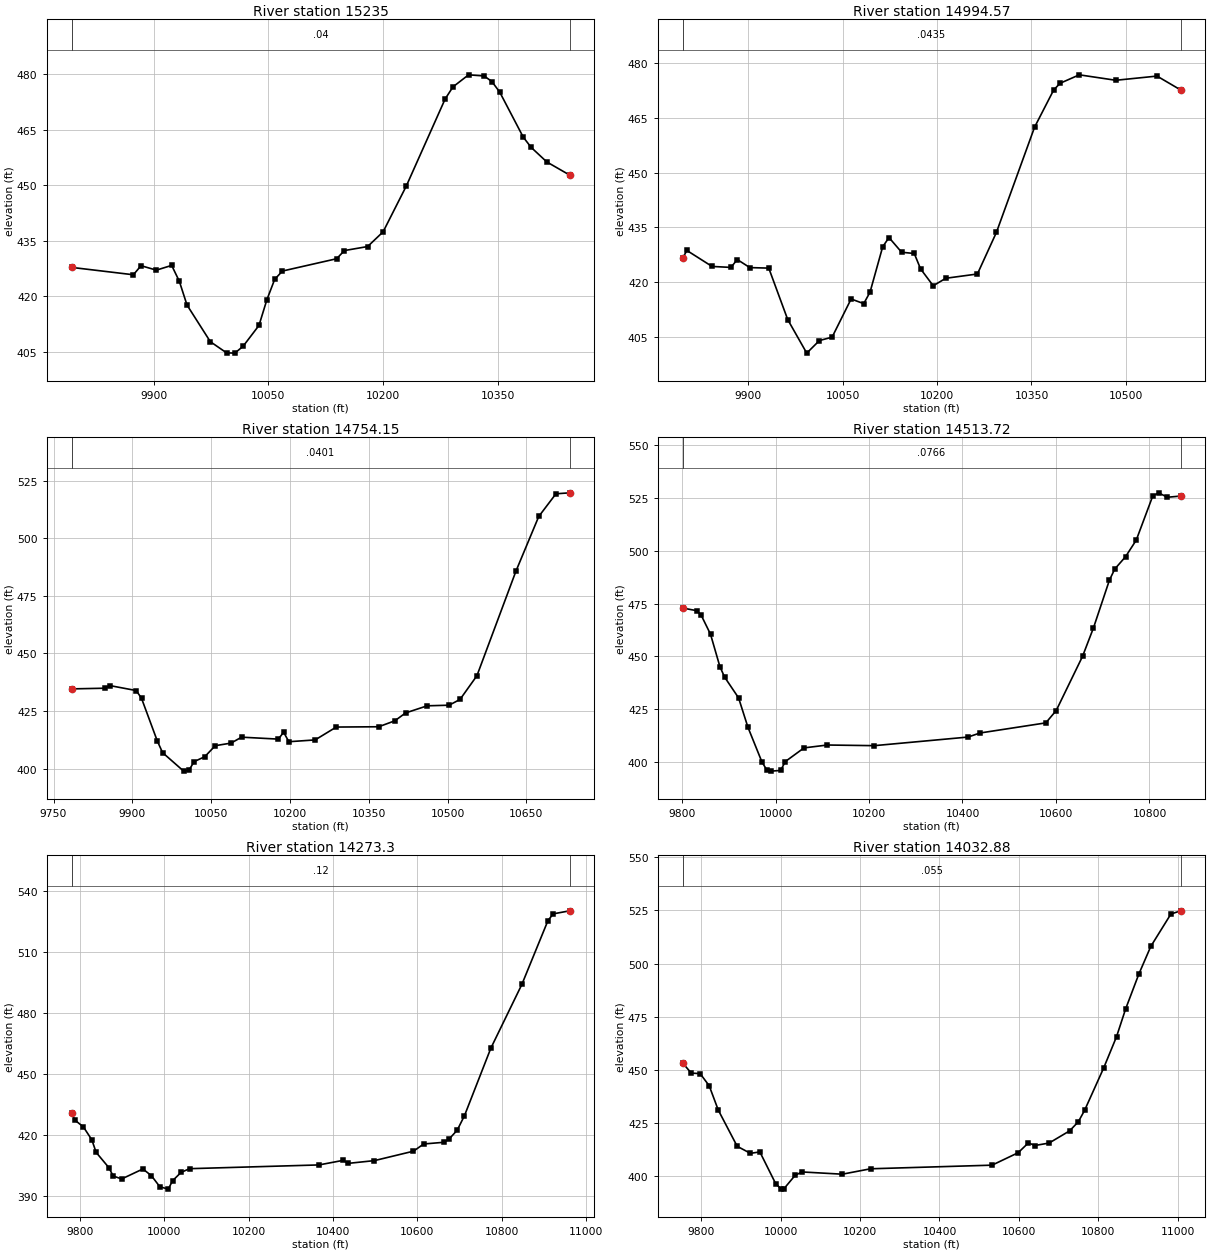
Type RM Length L Ch R = 1 ,   15235,240.423800,240.423800,240.423800
XS GIS Cut Line= 6
783724.337670469781463.010476279783876.384787829781452.567145753
783908.904876517781446.327706297783981.265084173781422.274206646
784171.133030637781391.462251154784363.954224601781350.354536488
#Sta/Elev= 30
9792.717427.75699873.569425.76619883.593428.2164 9903.64427.01319923.687428.2958
9933.711423.99229943.734417.58649974.259407.67669995.478404.662310006.32404.5865
 10017.1406.437810037.87412.066510048.19418.985710058.44424.531510068.57426.7695
10139.49 430.09910149.62432.304910180.01433.389910200.27437.368210230.66449.7669
 10281.5473.303210291.69476.543510312.06479.796910332.43479.491210342.61477.9718
 10352.8475.137610383.57462.972710393.86 460.20310414.43456.253910444.21452.7201
#Mann= 3 , 0 , 0
9792.717    0.04       09792.717    0.04       010444.21    0.04       0
#XS Ineff= 2 , 0
       0                   10113       0
Bank Sta=9792.717,10444.21
Exp/Cntr=0.3,0.1

Type RM Length L Ch R = 1 ,14994.57,240.423800,240.423800,240.423800
XS GIS Cut Line= 6
783718.073801466781686.421803828783849.614533958781681.674097475
783981.881355591781666.798306772784251.284147435781642.399817366
784401.735367293781614.289960698784501.034234051781587.588315217
#Sta/Elev= 30
9795.587426.43839802.514428.62919842.522424.24439872.551423.97559882.562426.1392
9902.583423.92719932.638423.78519962.807 409.6399992.975400.458910013.12403.9132
10033.26404.838710063.46415.317310083.52414.037710093.56417.209510113.62 429.637
10123.65432.169910143.72428.135810163.79427.798410173.82423.576210193.89418.9458
10213.95421.000710264.12422.170410294.31433.5846 10354.9462.441110385.28472.6583
10395.41474.495810426.01476.817410483.97475.322310549.47 476.473 10586.8472.6917
#Mann= 3 , 0 , 0
9795.587  0.0435       09795.587  0.0435       0 10586.8  0.0435       0
#XS Ineff= 2 , 0
       0                10090.49       0
Bank Sta=9795.587,10586.8
Exp/Cntr=0.3,0.1

Type RM Length L Ch R = 1 ,14754.15,240.423700,240.423700,240.423700
XS GIS Cut Line= 6
783712.108839327781899.172119911784081.989931564781921.184950028
784227.686719532781913.178374553784364.536548954781888.243908414
784453.146033914781862.788312737784638.466848943781787.913821679
#Sta/Elev= 30
9784.295434.6205 9847.26434.90789857.272436.04669907.396433.89519917.426430.5439
9947.518411.99839957.548 406.9579997.671398.9437 10007.7 399.33610017.72 403.089
10037.77405.191210057.82409.980310087.86411.103510107.87413.674610177.91412.8303
10187.92 415.81510197.92411.702210247.95412.483810288.13418.062610368.97418.1957
10399.63420.777710420.07424.189610461.33 427.28210502.95427.539610523.76430.0569
10555.88440.332110630.14485.691910673.55509.408810706.27519.248710732.24519.6713
#Mann= 3 , 0 , 0
9784.295  0.0401       09784.295  0.0401       010732.24  0.0401       0
#XS Ineff= 2 , 0
       0                10071.41       0
Bank Sta=9784.295,10732.24
Exp/Cntr=0.3,0.1

Type RM Length L Ch R = 1 ,14513.72,240.423800,240.423800,240.423800
XS GIS Cut Line= 6
783705.058998014782150.616459801784058.860575577782150.283454284
784233.083179396782127.061875911784378.867667895782080.760201784
784471.470119993782039.414536079784715.484989228781900.177551592
#Sta/Elev= 30
9801.055472.86029830.998471.63519840.998469.47619860.999460.4671    9881 445.203
9891.001440.25829921.002430.40279941.004416.52789971.005400.09759981.006396.4616
9991.006395.781910011.01396.118510021.01400.308410061.01406.763910111.02408.1239
10211.19407.814610411.83411.882610437.35413.797710578.26418.582810600.53424.4304
10656.93450.072710680.22463.484410714.34486.028510725.83491.308710748.79 497.101
10771.76504.963510806.93525.745310819.52527.302110838.42 525.20810866.43525.7713
#Mann= 3 , 0 , 0
9801.055  0.0766       09801.055  0.0766       010866.43  0.0766       0
#XS Ineff= 2 , 0
       0                10102.41       0
Bank Sta=9801.055,10866.43
Exp/Cntr=0.3,0.1

Type RM Length L Ch R = 1 , 14273.3,240.423800,240.423800,240.423800
XS GIS Cut Line= 6
783697.543842716782418.656998483784010.893043039782381.273377428
784082.909789953 782365.60180138784205.631105076782321.286685331
784406.510843212782206.899512142784756.358060324781959.755248446
#Sta/Elev= 30
9780.874431.04839788.432 427.4239808.705424.09699828.908417.68969838.994411.5265
9869.251403.98979879.337399.90629899.508398.41759949.788403.33639969.873400.0699
9989.957394.592710010.03393.417310020.07397.535710040.15401.635410060.33403.4824
10367.06405.329110424.48407.593310435.97 406.09210498.26407.452610590.79412.0979
10614.96415.636310663.58416.487810675.85418.236710694.34422.416610711.61429.5755
10773.97462.745210847.59494.208510909.43525.635310921.79 528.91910960.58530.4136
#Mann= 3 , 0 , 0
9780.874    0.12       09780.874    0.12       010960.58    0.12       0
#XS Ineff= 2 , 0
       09937.784        10163.33       0
Bank Sta=9780.874,10960.58
Exp/Cntr=0.3,0.1

Type RM Length L Ch R = 1 ,14032.88,240.423800,240.423800,240.423800
XS GIS Cut Line= 6
783775.431605826 782740.93349371783913.648695569782665.276053453
783978.457344281782623.309263215784171.756376358 782482.69778085
784582.515363545782136.216799955 784774.27158408781985.866486465
#Sta/Elev= 30
9752.452453.23449774.449448.38899796.931 448.1229819.682442.43089842.662430.9227
9890.308413.89579923.574410.58919947.402411.25169987.261396.296710001.51393.7297
10007.61393.807310036.01400.174410053.26401.829210155.17400.763110226.32403.3109
10532.47405.014710598.29410.880510624.23415.545710640.06414.265810676.13415.4273
10728.02421.180610749.94425.478410765.68430.834510813.95 450.87710846.14465.5141
10869.01478.564110902.08494.876510932.51508.056910983.05523.2721 11007.4524.8091
#Mann= 3 , 0 , 0
9752.452   0.055       09752.452   0.055       0 11007.4   0.055       0
#XS Ineff= 2 , 0
       0                10211.88       0
Bank Sta=9752.452,11007.4
Exp/Cntr=0.3,0.1

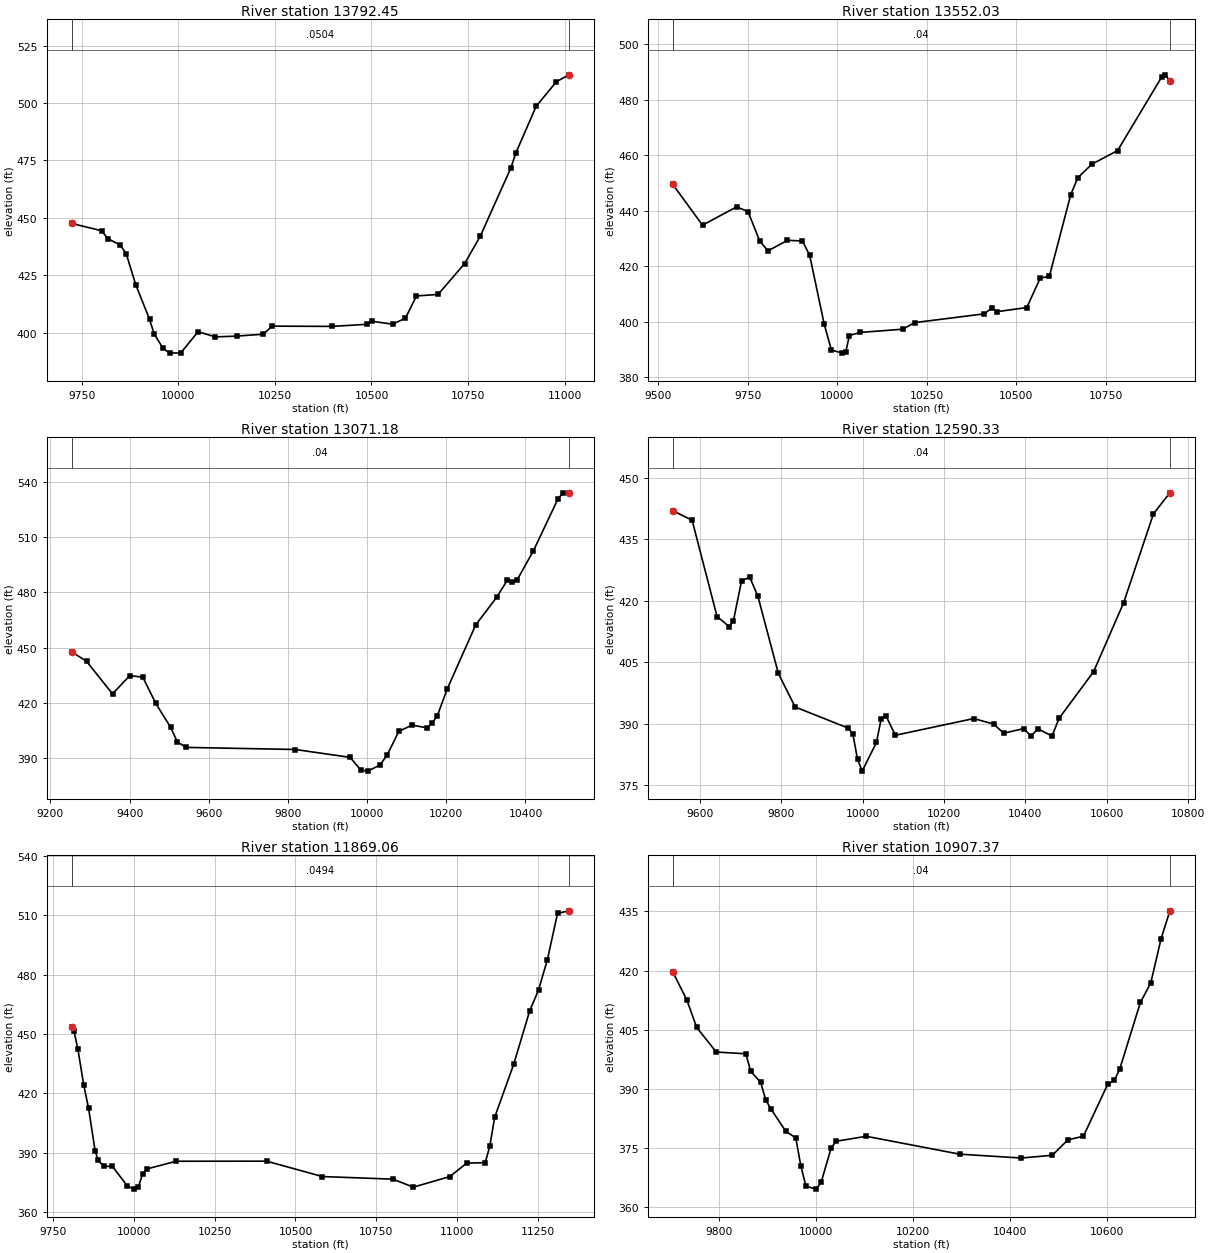
Type RM Length L Ch R = 1 ,13792.45,240.423700,240.423700,240.423700
XS GIS Cut Line= 6
783990.144525533783000.435301372784105.746830084782865.205709677
784282.435979296782538.172716066784377.400699096782401.608084703
784509.306485379782255.586971755784790.169800752782009.040158225
#Sta/Elev= 30
9723.393447.53569801.147444.35039817.476440.89439849.058 438.1639865.019434.3238
9889.655420.84799925.341405.79659937.033399.48459960.415393.1115 9977.49391.0373
10006.32391.123610051.08400.375410095.84398.1077 10151.8398.460810220.04399.2837
10242.92402.793910398.32402.680610487.54403.5815   10501404.923810554.83403.6479
10587.93406.240110616.49415.960410672.27416.578710741.07430.014110781.61441.9439
10860.74471.632910874.06478.314810926.39 498.56210978.51509.2084 11010.8512.2579
#Mann= 3 , 0 , 0
9723.393  0.0504       09723.393  0.0504       0 11010.8  0.0504       0
#XS Ineff= 2 , 0
       09953.384                       0
Bank Sta=9723.393,11010.8
Exp/Cntr=0.3,0.1

Type RM Length L Ch R = 1 ,13552.03,480.847600,480.847600,480.847600
XS GIS Cut Line= 6
784145.094314508783201.452039519784292.798129776783090.194589957
784349.850459232783004.537635885784409.679892513782634.866940737
784498.813736087782419.171981658784822.231137007782055.773631413
#Sta/Elev= 30
9540.909449.47819624.161434.72849719.457441.3373 9751.24439.61249783.348 429.158
9806.698425.46759861.309429.2649 9902.98429.03879923.295423.83449963.643399.1333
9983.728389.781910013.83388.625410023.86388.970810033.89394.969410063.97396.0845
10182.93397.244210216.09399.618910410.35402.782610432.26404.951210444.94403.5412
10528.97405.051110566.65415.647110592.11416.3265 10651.7445.697810671.39451.8243
10710.91456.719410782.43461.617410905.18488.040810914.65488.901910928.41486.8153
#Mann= 3 , 0 , 0
9540.909    0.04       09540.909    0.04       010928.41    0.04       0
#XS Ineff= 2 , 0
       0                               0
Bank Sta=9540.909,10928.41
Exp/Cntr=0.3,0.1

Type RM Length L Ch R = 1 ,13071.18,480.847500,480.847500,480.847500
XS GIS Cut Line= 6
784160.301930467783245.988629112784544.507765308783079.286986326
784767.001114042783016.438510016784809.789512178 782998.58950797
784904.770946028782900.036659802785235.377359223782637.972467981
#Sta/Elev= 30
9253.369447.85239291.297442.57989356.884424.93769400.608434.83259433.401434.0025
9466.195419.7564 9503.43406.8472 9520.85398.82579542.712395.88169819.029394.7353
9956.879390.46889984.259383.577410001.49 382.99410032.39386.295910050.68391.7504
10080.04404.561510113.31407.972610151.84 406.49610164.64409.165210177.23413.0245
 10202.4427.654410274.26462.396910328.25477.668910353.56486.517810366.38 485.513
10379.21486.938210420.16502.701910482.42530.979110495.59534.077810509.27534.0837
#Mann= 3 , 0 , 0
9253.369    0.04       09253.369    0.04       010509.27    0.04       0
#XS Ineff= 2 , 0
       09659.522                       0
Bank Sta=9253.369,10509.27
Exp/Cntr=0.3,0.1

Type RM Length L Ch R = 1 ,12590.33,721.271300,721.271300,721.271300
XS GIS Cut Line= 6
  784178.9163156783300.502185569784436.248119894783274.984178623
784561.687254944783318.075976293784758.920288833783431.694509293
784867.170893252783432.270906389785267.852458805783147.039961413
#Sta/Elev= 30
9533.213 442.0479580.981439.71239642.269416.17459672.457413.7168 9682.52415.1542
9702.625424.95969722.625425.76789742.626 421.1459792.954402.2721 9834.15394.0918
9964.784388.92169976.063387.42839987.467381.29449998.942378.424510033.86385.4194
10045.51 391.15110057.15391.958510080.45387.186210272.76391.260210321.86389.9395
10346.41387.685110395.51 388.80810413.63387.012710430.88388.758110465.36386.9864
10482.61  391.3110567.36402.697510641.01419.470110714.66441.290410754.98446.3989
#Mann= 3 , 0 , 0
9533.213    0.04       09533.213    0.04       010754.98    0.04       0
#XS Ineff= 2 , 0
       0                10113.74       0
Bank Sta=9533.213,10754.98
Exp/Cntr=0.3,0.1

Type RM Length L Ch R = 1 ,11869.06,961.695100,961.695100,961.695100
XS GIS Cut Line= 6
 784420.39018271784150.005453022784695.814556358 783913.86011402
 785095.22138633783659.659672316785264.105774692783530.294204216
 785461.27333333783348.182863008785607.128095027783183.255376576
#Sta/Elev= 30
9807.335453.48889814.869451.47029826.884442.52169844.971424.29979860.021412.5759
9880.405390.91919890.123386.15289907.166383.20789933.927383.14339980.428373.1958
 10000.8371.688410014.06372.719610027.31379.451910041.15381.909610131.29385.7649
10410.66385.798910583.46 378.03610801.39376.718110864.73372.6883 10977.5378.0307
11030.08384.844911087.03385.024711101.23393.452111116.28407.991611174.92434.6265
11224.59461.734411251.77472.114611279.24487.490111310.63510.878111345.36 512.152
#Mann= 3 , 0 , 0
9807.335  0.0494       09807.335  0.0494       011345.36  0.0494       0
#XS Ineff= 2 , 0
       09948.928        10196.46       0
Bank Sta=9807.335,11345.36
Exp/Cntr=0.3,0.1

Type RM Length L Ch R = 1 ,10907.37,240.423800,240.423800,240.423800
XS GIS Cut Line= 6
785525.804628004784394.192580409785501.145591255784228.058828099
785488.616729738784174.934551235785446.997624841784035.435533075
785485.171274036783795.600800574785629.839068607783408.000294261
#Sta/Elev= 30
9704.589419.71639733.921412.49459754.093405.58719794.495399.3508 9855.39398.9121
9865.568394.44499886.049391.65719896.324387.27549906.598385.02069937.561379.3209
 9958.39377.56919968.805370.4721 9979.22365.391710000.06364.631410010.52366.3237
10031.43375.142210041.88376.767210103.61378.0122   10296373.488910423.03372.5089
10487.07373.206210519.09377.107510551.11378.033210601.13 391.16810615.15392.2605
10625.83394.977510668.52411.915910689.87 416.82210711.22428.047610729.36 435.115
#Mann= 3 , 0 , 0
9704.589    0.04       09704.589    0.04       010729.36    0.04       0
#XS Ineff= 2 , 0
       0                10262.75       0
Bank Sta=9704.589,10729.36
Exp/Cntr=0.3,0.1

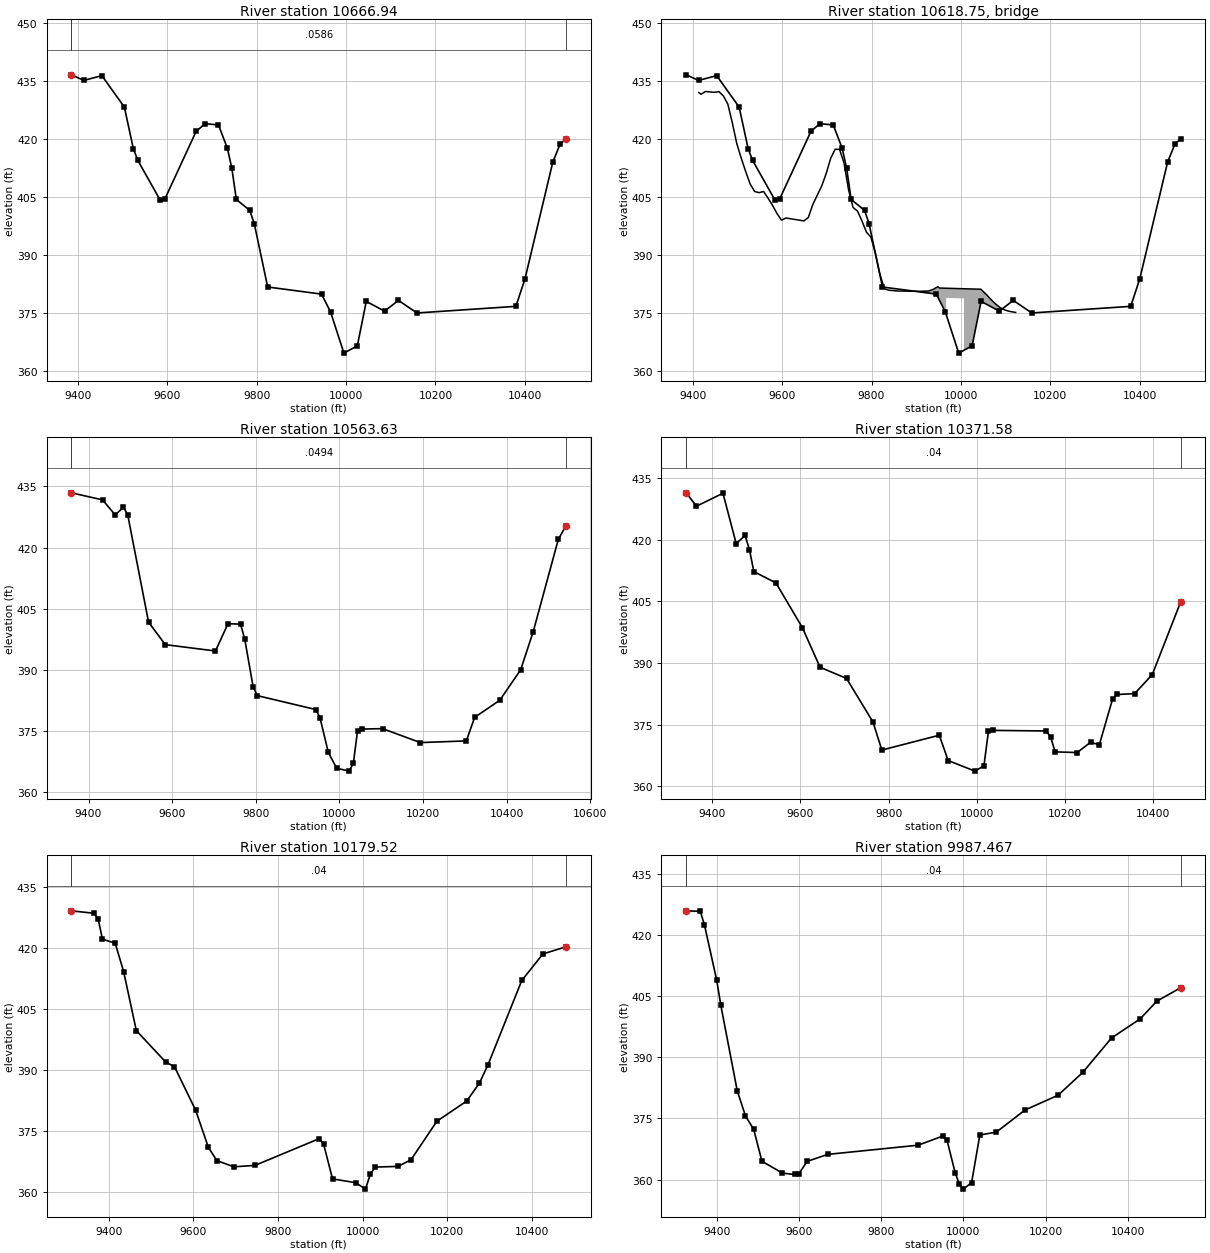
Type RM Length L Ch R = 1 ,10666.94,103.313900,103.313900,103.313900
XS GIS Cut Line= 6
 785692.06272377784682.458944726 785720.43467924784304.819922626
785701.532831967784009.317100659785662.829192698783793.147031501
785673.699366331783667.350317061785699.640058666783587.756053656
#Sta/Elev= 30
9385.316436.6848 9413.13435.24519453.576436.47199503.878 428.3219523.998417.5491
9534.059414.51499584.289404.20039594.304404.50959664.408422.04039684.412424.0378
9714.412 423.7189734.412417.66289744.412412.44819754.412404.43039784.448401.6078
9794.467398.19829824.522381.77619945.078379.93359965.127375.34249995.142364.6623
10025.16366.559910045.17  378.0510086.06375.526110117.15 378.308 10158.6375.0546
10379.93376.768610400.23383.863210462.66414.1543 10478.8418.727910491.82420.1075
#Mann= 3 , 0 , 0
9385.316  0.0586       09385.316  0.0586       010491.82  0.0586       0
#XS Ineff= 2 , 0
       09905.265         10258.8       0
Bank Sta=9385.316,10491.82
Exp/Cntr=0.3,0.1

Type RM Length L Ch R = 3 ,10618.75,,,
BEGIN DESCRIPTION:
END DESCRIPTION:
Bridge Culvert--1,0,-1,-1, 0
Deck Dist Width WeirC Skew NumUp NumDn MinLoCord MaxHiCord MaxSubmerge Is_Ogee
35.156950,33.000000,2.6,0, 57, 57, , , 0.95, 0, 0,0,,
 9413.60 9418.57 9428.57 9448.57 9458.57 9468.57 9478.57 9488.57 9498.57 9508.57
 9518.57 9528.57 9538.57 9548.57 9558.57 9568.57 9578.57 9588.57 9598.57 9608.57
 9648.57 9658.57 9668.57 9688.57 9698.57 9708.57 9718.57 9728.57 9738.57 9748.57
 9758.57 9768.57 9778.57 9788.57 9798.57 9808.57 9818.57 9828.57 9838.57 9858.58
 9908.59 9928.60 9938.60 9948.60 9951.69 9966.89 9966.8910006.8910006.8910044.75
10058.6510068.6710078.6910088.7010098.7210108.2710122.55
  432.09  431.66  432.37  432.15  432.34  431.21  429.10  424.25  418.87  415.10
  411.62  408.40  406.48  406.20  406.49  404.75  402.89  400.78  399.08  399.63
  398.88  399.76  403.11  407.92  411.14  415.05  417.42  417.39  413.81  406.97
  402.37  401.44  398.90  395.98  394.68  390.54  385.18  381.34  380.95  380.74
  380.66  380.76  381.21  381.87  381.51  381.46  381.46  381.32  381.32  381.20
  379.63  378.37  377.28  376.36  375.81  375.48  375.20
 -567.91 -568.34 -567.63 -567.85 -567.66 -568.79 -570.90 -575.75 -581.13 -584.90
 -588.38 -591.60 -593.52 -593.80 -593.51 -595.25 -597.11 -599.22 -600.92 -600.37
 -601.12 -600.24 -596.89 -592.08 -588.86 -584.95 -582.58 -582.61 -586.19 -593.03
 -597.63 -598.56 -601.10 -604.02 -605.32 -609.46 -614.82 -618.66 -619.05 -619.26
 -619.34 -619.24 -618.79 -618.13 -618.49 -618.54  378.96  378.82 -618.68 -618.80
 -620.37 -621.63 -622.72 -623.64 -624.19 -624.52 -624.80
 9413.60 9418.57 9428.57 9448.57 9458.57 9468.57 9478.57 9488.57 9498.57 9508.57
 9518.57 9528.57 9538.57 9548.57 9558.57 9568.57 9578.57 9588.57 9598.57 9608.57
 9648.57 9658.57 9668.57 9688.57 9698.57 9708.57 9718.57 9728.57 9738.57 9748.57
 9758.57 9768.57 9778.57 9788.57 9798.57 9808.57 9818.57 9828.57 9838.57 9858.58
 9908.59 9928.60 9938.60 9948.60 9951.69 9982.45 9982.4510022.4510022.4510044.75
10058.6510068.6710078.6910088.7010098.7210108.2710122.55
  432.09  431.66  432.37  432.15  432.34  431.21  429.10  424.25  418.87  415.10
  411.62  408.40  406.48  406.20  406.49  404.75  402.89  400.78  399.08  399.63
  398.88  399.76  403.11  407.92  411.14  415.05  417.42  417.39  413.81  406.97
  402.37  401.44  398.90  395.98  394.68  390.54  385.18  381.34  380.95  380.74
  380.66  380.76  381.21  381.87  381.51  381.40  381.40  381.27  381.27  381.20
  379.63  378.37  377.28  376.36  375.81  375.48  375.20
 -567.91 -568.34 -567.63 -567.85 -567.66 -568.79 -570.90 -575.75 -581.13 -584.90
 -588.38 -591.60 -593.52 -593.80 -593.51 -595.25 -597.11 -599.22 -600.92 -600.37
 -601.12 -600.24 -596.89 -592.08 -588.86 -584.95 -582.58 -582.61 -586.19 -593.03
 -597.63 -598.56 -601.10 -604.02 -605.32 -609.46 -614.82 -618.66 -619.05 -619.26
 -619.34 -619.24 -618.79 -618.13 -618.49 -618.60  378.90  378.77 -618.73 -618.80
 -620.37 -621.63 -622.72 -623.64 -624.19 -624.52 -624.80
BR Coef=-1 , 0 , 0 ,, 0 ,,,0.8,0,1,0,
WSPro=,,,, 1 ,,,, 0 ,,,, 0 ,,,,-1 ,-1 ,-1 , 0 , 0 , 0 , 0 , 0
BC Design=,, 0 ,, 0 ,,,,,,

Type RM Length L Ch R = 1 ,10563.63,192.054200,192.054200,192.054200
XS GIS Cut Line= 4
785796.164004534784729.654496044785804.538550198784144.761083767
785803.400365502784022.406225085785784.835219413783546.929332227
#Sta/Elev= 30
9358.945433.41019433.607431.6791 9463.61428.01129483.612 429.8469493.613428.0693
9543.618401.72219583.623396.21539703.635394.66119733.638401.35599763.641401.2346
9773.642397.59629793.644385.95769803.645383.72759943.659380.3192 9953.66378.3363
9973.661369.82139993.662365.942510023.66365.229310033.66367.197410043.66375.1635
10053.66375.535610103.69375.631310193.76372.224310303.85372.632210323.86378.4096
10383.91382.586910433.94390.063710463.97399.405810524.01422.0273 10542.1425.2809
#Mann= 3 , 0 , 0
9358.945  0.0494       09358.945  0.0494       0 10542.1  0.0494       0
#XS Ineff= 2 , 0
       09921.169        10265.49       0
Bank Sta=9358.945,10542.1
Exp/Cntr=0.3,0.1

Type RM Length L Ch R = 1 ,10371.58,192.054200,192.054200,192.054200
XS GIS Cut Line= 6
785999.601908349784708.262278578786011.461023894784293.073300908
786008.630519982784177.668412901785968.610376398783882.070851506
785963.887779607783803.650081203785962.380282961783590.630612498
#Sta/Elev= 30
 9341.01431.48419364.304 428.2219424.354431.38469454.372419.09979474.385421.0958
9484.391417.66439494.397412.26989544.428409.52659604.443398.60489644.449388.9569
9704.459 386.234 9764.47375.60019784.476368.77489914.731372.38669934.838366.2089
9995.605363.634610015.92364.943110026.08373.296510036.23373.564310157.28373.4234
10167.34371.864810177.36368.328510227.45368.165310257.49370.6683 10277.5370.0663
 10307.5381.2147 10317.5382.316810357.51382.522810397.52387.1771 10461.9404.9024
#Mann= 3 , 0 , 0
 9341.01    0.04       0 9341.01    0.04       0 10461.9    0.04       0
#XS Ineff= 2 , 0
       09848.556        10156.07       0
Bank Sta=9341.01,10461.9
Exp/Cntr=0.3,0.1

Type RM Length L Ch R = 1 ,10179.52,192.054100,192.054100,192.054100
XS GIS Cut Line= 6
786094.076545534784728.321961814786126.299761606784217.190567174
 786151.61238358784110.366160287  786198.6267592784017.980324405
786231.341053942783906.670032199786248.193116554783580.774997555
#Sta/Elev= 30
 9311.57429.02829364.957428.42879374.969426.96499384.982422.05369415.018421.0859
9435.043414.11679465.079399.59019535.165391.79169555.189390.74919605.251380.0438
9635.287370.92999655.312367.65969695.382366.1242 9745.54366.45739897.649373.0465
9908.084371.60129928.953363.14349983.778362.217510006.84360.632710018.22364.2623
 10029.6366.0568 10083.5366.212510114.46367.840710175.72377.327810246.23 382.283
 10276.3386.711710296.34391.143710376.42411.927110426.42418.433310480.66420.1791
#Mann= 3 , 0 , 0
 9311.57    0.04       0 9311.57    0.04       010480.66    0.04       0
#XS Ineff= 2 , 0
       09813.783        10061.74       0
Bank Sta=9311.57,10480.66
Exp/Cntr=0.3,0.1

Type RM Length L Ch R = 1 ,9987.467,192.054200,192.054200,192.054200
XS GIS Cut Line= 6
 786334.00900477784779.266525073786355.862092122784207.901618939
786354.376749055784032.175832696786369.352050485783804.593841504
786369.060013516 783705.33590567786361.145321559783576.880093937
#Sta/Elev= 30
9325.216 425.9099359.502425.79049369.507422.52299399.524408.8847 9409.53 402.746
9449.552381.75359469.563 375.6129489.574372.32869509.586364.51049559.614361.5988
 9589.63361.26519599.636361.47599619.647364.48399669.676366.19599889.903368.4481
9949.914370.69519959.919369.73959979.929361.67589989.934358.9623 9999.94357.6772
10019.95 359.28510039.96370.947310079.98371.648910150.18377.088910230.41380.6984
10290.47386.288810360.48394.730810430.51399.433210470.56403.750710528.87407.0512
#Mann= 3 , 0 , 0
9325.216    0.04       09325.216    0.04       010528.87    0.04       0
#XS Ineff= 2 , 0
       09830.646        10058.38       0
Bank Sta=9325.216,10528.87
Exp/Cntr=0.3,0.1

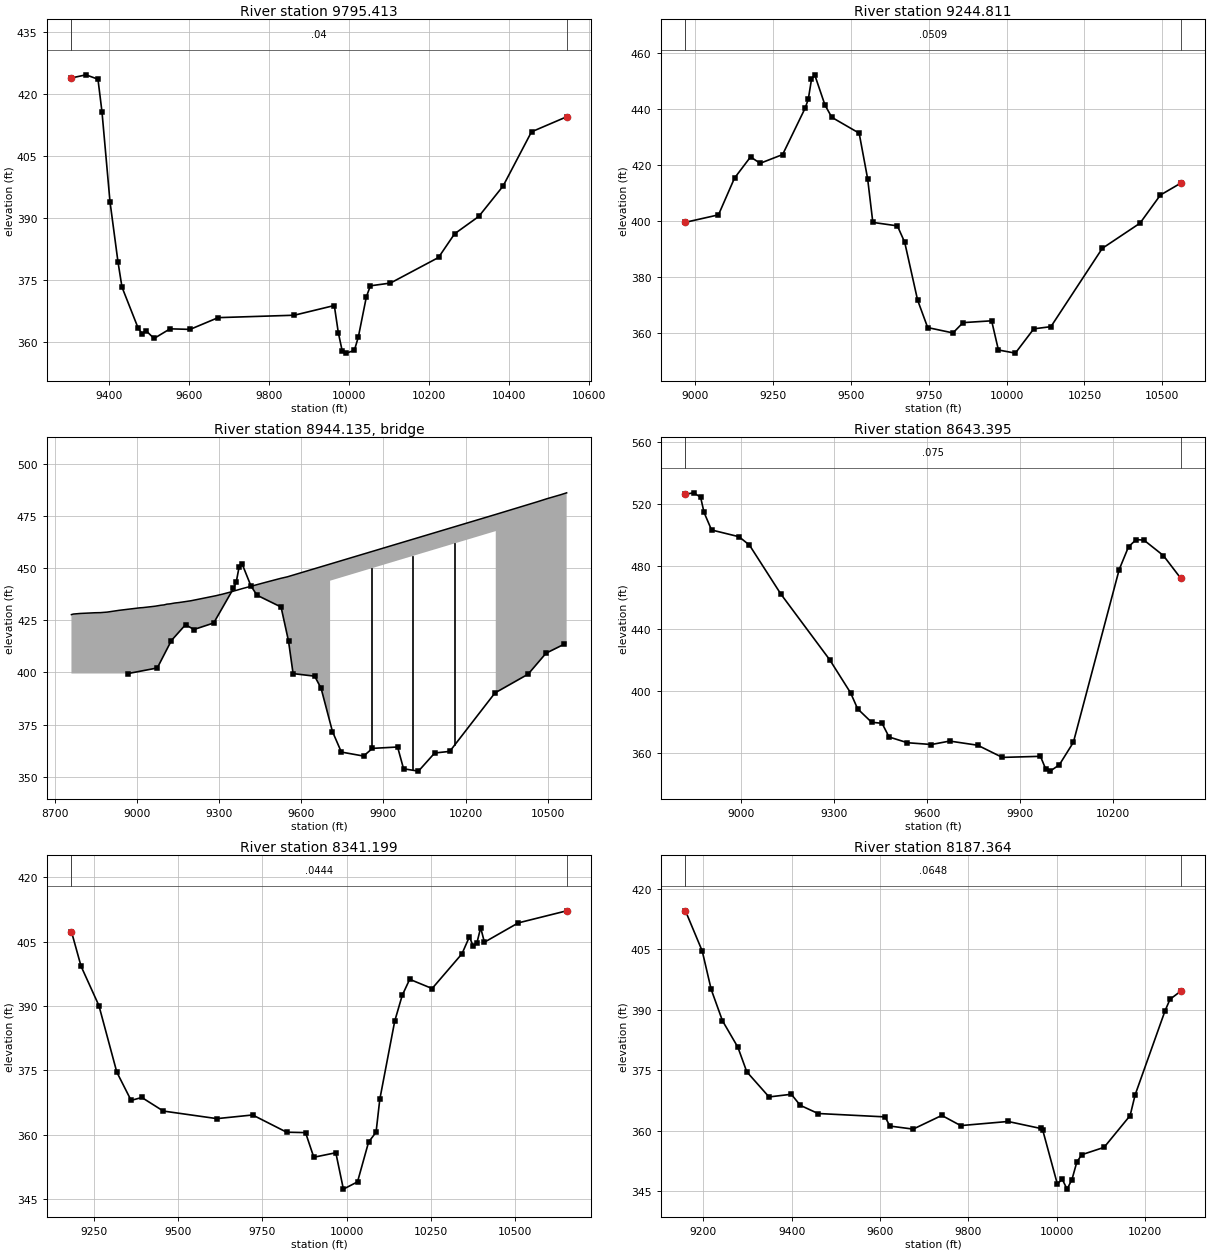
Type RM Length L Ch R = 1 ,9795.413,550.601800,550.601800,550.601800
XS GIS Cut Line= 6
786555.204444171784801.262704649786545.145621467784303.714110455
786548.600257923784020.462603118786544.849764864783902.575963546
786521.807555189783709.690560671786495.747675085783568.774705062
#Sta/Elev= 30
9306.917423.93549343.182424.69619373.184 423.6359383.185415.74849403.186393.9554
9423.187 379.3329433.188373.2229 9473.19363.36789483.192361.94229493.196362.6634
9513.202360.78639553.214 363.119 9603.23 362.9869673.252365.83319863.293366.4175
9963.306368.77159973.308362.19279983.311357.64429993.313  357.2310013.32357.8889
10023.32361.141110043.32370.856510053.32373.549810103.34 374.21110223.47380.4129
10263.64386.158210324.04390.367710384.66397.724110455.68410.875610543.44414.5197
#Mann= 3 , 0 , 0
9306.917    0.04       09306.917    0.04       010543.44    0.04       0
#XS Ineff= 2 , 0
       09806.564                       0
Bank Sta=9306.917,10543.44
Exp/Cntr=0.3,0.1

Type RM Length L Ch R = 1 ,9244.811,601.415900,601.415900,601.415900
XS GIS Cut Line= 5
787465.798382401784877.952637449787365.429680407784475.273575455
787256.426899403784235.323170319786812.329531699 783667.66053988
786695.168102413783516.039866671
#Sta/Elev= 30
8968.055399.47069074.157402.12939125.687415.28419177.217422.86059208.135420.5806
9280.276423.70629352.418440.26969362.724443.5048 9373.03450.60619383.354452.2352
9416.305 441.4269438.272437.02979526.139431.3605 9553.34415.07159570.073399.4325
9648.918398.19359672.406392.34279713.835  371.659746.294361.8039 9827.44359.8852
9859.899363.57259951.731364.22259973.504353.777710027.91352.658310087.11361.3501
10142.18362.126810307.24390.149410428.39399.157910493.81409.215610558.95 413.454
#Mann= 3 , 0 , 0
8968.055  0.0509       08968.055  0.0509       010558.95  0.0509       0
#XS Ineff= 2 , 0
       09843.351        10115.62       0
Bank Sta=8968.055,10558.95
Exp/Cntr=0.3,0.1

Type RM Length L Ch R = 3 ,8944.135,,,
BEGIN DESCRIPTION:
END DESCRIPTION:
Bridge Culvert--1,0,-1,-1, 0
Deck Dist Width WeirC Skew NumUp NumDn MinLoCord MaxHiCord MaxSubmerge Is_Ogee
205.707950,190.000000,2.6,0, 32, 31, , , 0.95, 0, 0,0,,
 8760.66 8767.38 8792.13 8847.19 8866.38 8891.13 8934.65 9011.17 9022.10 9065.83
 9087.70 9098.63 9109.56 9120.49 9138.62 9153.29 9197.02 9287.11 9311.86 9339.13
 9382.86 9470.32 9524.98 9548.93 9705.17 9705.1710310.1710310.1710462.2210498.08
10547.7710569.04
  427.73  427.99  428.27  428.62  428.67  428.93  429.78  430.99  431.09  431.75
  432.23  432.38  432.75  432.88  433.30  433.51  434.37  436.76  437.52  438.47
  440.13  443.23  445.12  445.84  451.98  451.98  475.78  475.78  481.85  483.35
  485.24  486.13
 -572.27 -572.01 -571.73 -571.38 -571.33 -571.07 -570.22 -569.01 -568.91 -568.25
 -567.77 -567.62 -567.25 -567.12 -566.70 -566.49 -565.63 -563.24 -562.48 -561.53
 -559.87 -556.77 -554.88 -554.16 -548.02  443.98  467.78 -524.22 -518.15 -516.65
 -514.76 -513.87
 8760.66 8767.38 8792.13 8847.19 8866.38 8891.13 8934.65 9011.17 9022.10 9065.83
 9087.70 9098.63 9109.56 9120.49 9138.62 9153.29 9197.02 9306.34 9470.32 9524.98
 9548.93 9588.24 9588.2410193.2410193.2410289.3610364.4410462.2210498.0810547.77
10569.04
  427.73  427.99  428.27  428.62  428.67  428.93  429.78  430.99  431.09  431.75
  432.23  432.38  432.75  432.88  433.30  433.51  434.37  437.33  443.23  445.12
  445.84  447.38  447.38  471.16  471.16  474.93  477.99  481.85  483.35  485.24
  486.13
 -572.27 -572.01 -571.73 -571.38 -571.33 -571.07 -570.22 -569.01 -568.91 -568.25
 -567.77 -567.62 -567.25 -567.12 -566.70 -566.49 -565.63 -562.67 -556.77 -554.88
 -554.16 -552.62  439.38  463.16 -528.84 -525.07 -522.01 -518.15 -516.65 -514.76
 -513.87
Pier Skew, UpSta & Num, DnSta & Num=  ,9855.42, 2 ,9738.49, 2 , 0 , 0 , 0 ,,
    4.00    4.00
 -542.12  457.88
    4.00    4.00
 -546.71  453.29
Pier Skew, UpSta & Num, DnSta & Num=  ,10007.67, 2 ,9890.74, 2 , 0 , 0 , 0 ,,
    4.00    4.00
 -536.13  463.87
    4.00    4.00
 -540.73  459.27
Pier Skew, UpSta & Num, DnSta & Num=  ,10159.92, 2 ,10042.99, 2 , 0 , 0 , 0 ,,
    4.00    4.00
 -530.15  469.85
    4.00    4.00
 -534.75  465.25
BR Coef=-1 , 0 , 0 ,, 0 ,,,0.8,0,1,0,
WSPro=,,,, 1 ,,,, 0 ,,,, 0 ,,,,-1 ,-1 ,-1 , 0 , 0 , 0 , 0 , 0
BC Design=,, 0 ,, 0 ,,,,,,

Type RM Length L Ch R = 1 ,8643.395,302.196300,302.196300,302.196300
XS GIS Cut Line= 6
788043.754356861784498.383636206787732.904267754783898.243929482
787609.107799391783728.279901559787532.140279383783637.876122623
787349.600073082783438.881894966787156.215664968783180.276967826
#Sta/Elev= 30
8819.219526.33738845.554 527.2158868.077524.45268879.339514.60028903.481503.3712
8991.957499.04359025.743493.66629127.099462.22989284.765420.03849352.335398.7388
9374.859388.55099419.906379.93699453.692379.25229476.215370.47899535.318 366.795
9613.093365.64939671.854367.85929762.264365.18539841.747357.37239964.723358.0656
9981.366350.08219996.057348.562510025.67352.615610070.96 367.04710218.78477.9465
 10248.9492.574810273.87497.219710298.84 496.82210361.28486.970910417.12472.4367
#Mann= 3 , 0 , 0
8819.219   0.075       08819.219   0.075       010417.12   0.075       0
#XS Ineff= 2 , 0
       0                               0
Bank Sta=8819.219,10417.12
Exp/Cntr=0.3,0.1

Type RM Length L Ch R = 1 ,8341.199,153.834900,153.834900,153.834900
XS GIS Cut Line= 6
787977.542357057784131.898269743787795.250690401783619.745491967
787674.497341061783384.177409429787660.902953046783339.637553215
787489.261107057782981.724658623787391.604857057782786.412158623
#Sta/Elev= 30
9183.312407.36959211.863 399.2949264.936390.10519318.008374.61319360.467368.0222
 9392.31368.70049455.998  365.549615.216363.77399721.362364.6263 9822.17360.6132
9878.356360.51579902.864354.77519968.254355.82699990.729347.348110032.62349.0392
10065.55358.315710087.73360.612110098.82368.279610143.18386.514810165.36 392.493
10187.54396.237110254.08 394.08710342.81 402.18810364.99406.168510376.08403.9195
10387.17404.722910398.26408.271110409.35404.876710509.76409.377510653.53412.1917
#Mann= 3 , 0 , 0
9183.312  0.0444       09183.312  0.0444       010653.53  0.0444       0
#XS Ineff= 2 , 0
       09892.121                       0
Bank Sta=9183.312,10653.53
Exp/Cntr=0.3,0.1

Type RM Length L Ch R = 1 ,8187.364,88.183500,88.183500,88.183500
XS GIS Cut Line= 6
 788025.28541261 784142.74896419787971.031940401783704.380908623
787870.219011188783438.105244711 787845.21259439783391.093181118
787751.188467264783184.540178388787698.450454329783083.687618443
#Sta/Elev= 30
9159.588414.49249197.624404.52579217.777395.05379243.328387.27689278.235380.7084
9298.387374.62379348.769368.3969 9399.15369.05969419.303366.32789459.608364.2942
9611.331 363.4569622.024361.18699674.821360.42969739.643363.82019782.414361.2985
9889.538  362.32 9963.64360.58479968.008360.177810001.05 346.82810012.06348.0212
10023.08345.565310034.09347.9355 10045.1352.259410056.12354.083210106.82355.9153
10165.72363.782810176.99368.8956 10244.7389.722510255.98392.585110280.04394.5821
#Mann= 3 , 0 , 0
9159.588  0.0648       09159.588  0.0648       010280.04  0.0648       0
#XS Ineff= 2 , 0
       09944.937        10066.05       0
Bank Sta=9159.588,10280.04
Exp/Cntr=0.3,0.1