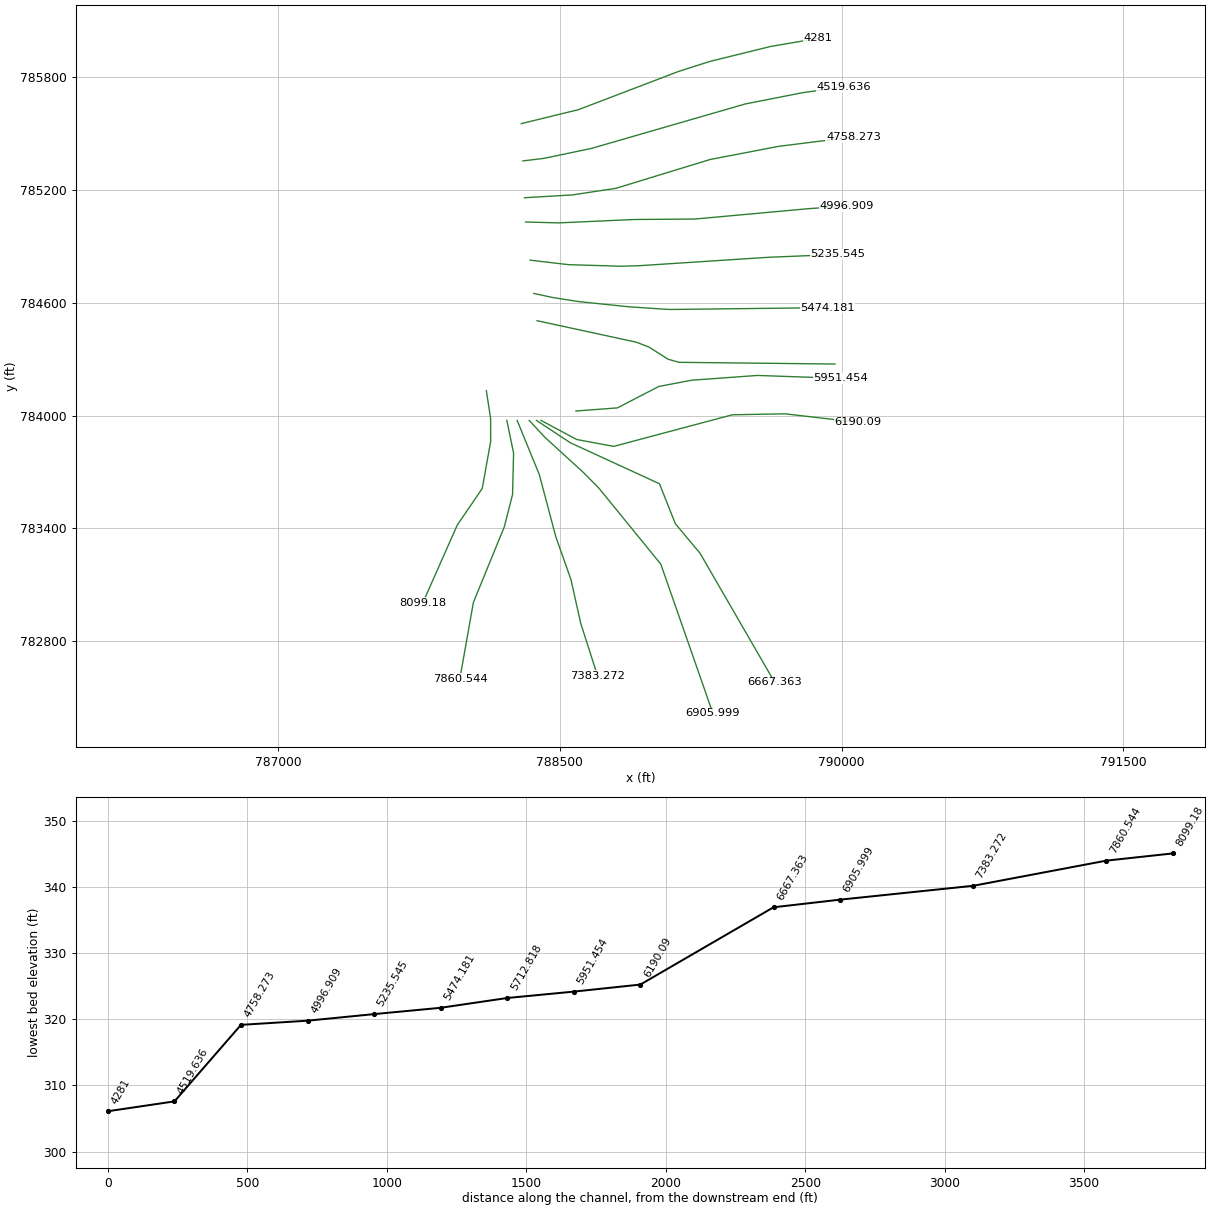
HEC-RAS study 17521_ras.prj: 17521

--- 17521_ras.g01 (geometry) --- (continued)

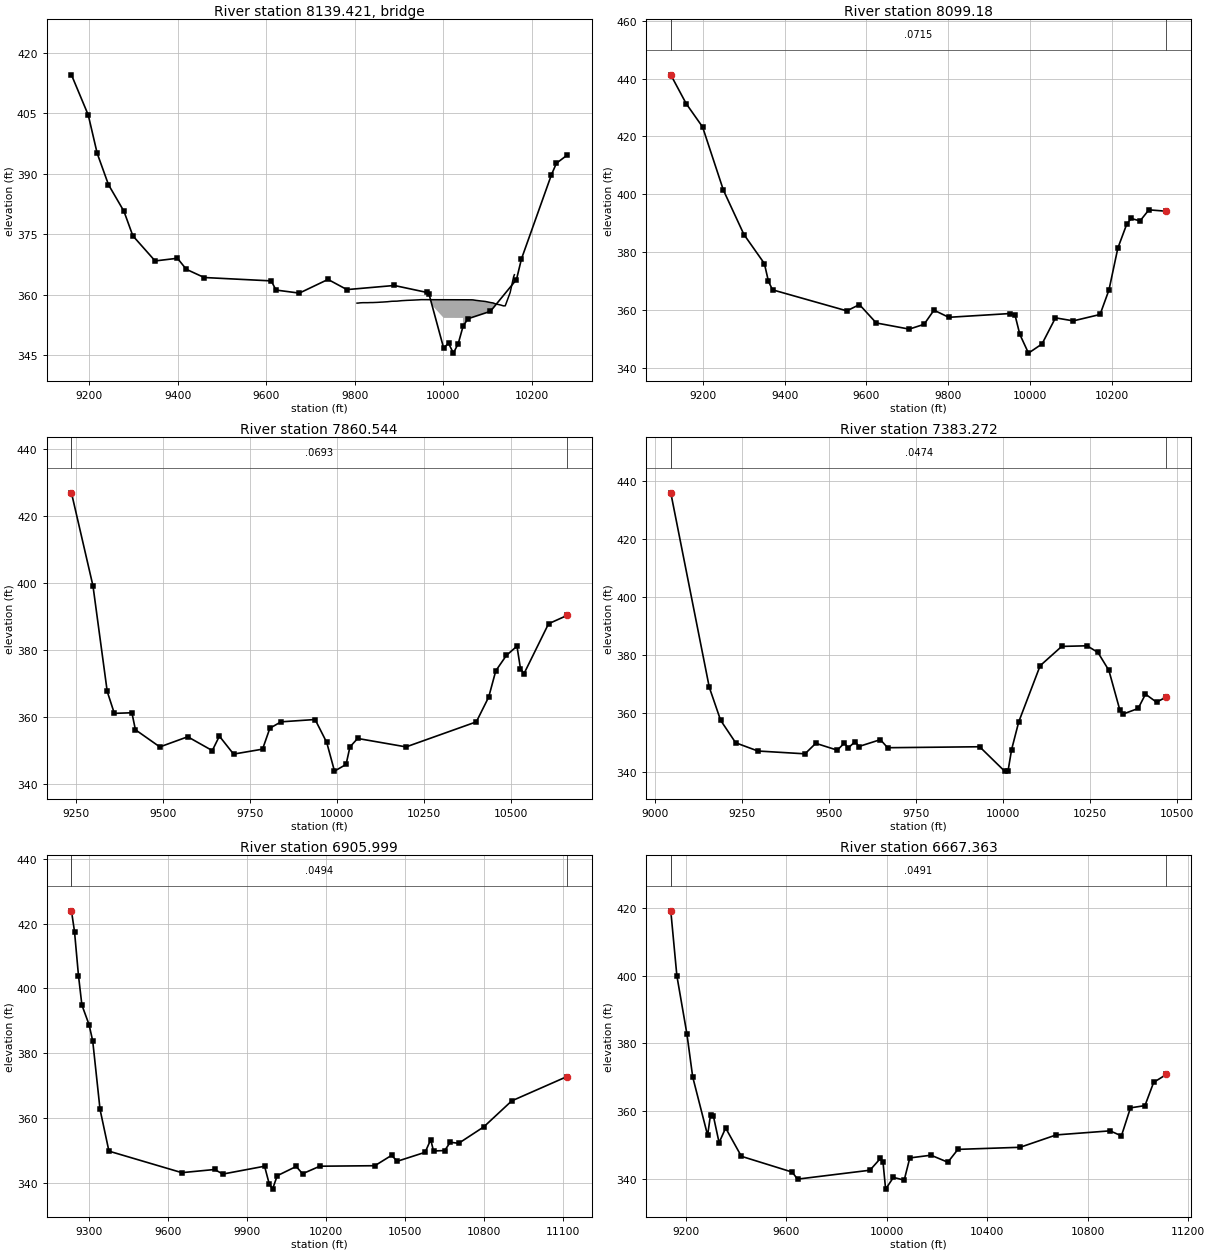
Type RM Length L Ch R = 3 ,8139.421,,,
BEGIN DESCRIPTION:
END DESCRIPTION:
Bridge Culvert--1,0,-1,-1, 0
Deck Dist Width WeirC Skew NumUp NumDn MinLoCord MaxHiCord MaxSubmerge Is_Ogee
29.591750,29.000000,2.6,0, 42, 42, , , 0.95, 0, 0,0,,
 9805.24 9807.67 9812.14 9818.66 9829.65 9836.25 9840.64 9851.63 9860.37 9862.62
 9873.61 9884.48 9884.59 9895.58 9906.57 9908.59 9917.56 9928.55 9932.70 9939.54
 9943.84 9950.30 9974.76 9974.7610044.7610044.7610064.4110067.6710073.6310084.81
10090.0310095.3910095.9910107.0710113.0210118.1610129.2410136.1910140.3310151.41
10159.3710161.01
  357.95  357.96  358.02  358.06  358.06  358.09  358.09  358.14  358.20  358.21
  358.29  358.41  358.41  358.44  358.56  358.57  358.63  358.68  358.70  358.74
  358.76  358.81  358.80  358.80  358.78  358.78  358.77  358.75  358.64  358.49
  358.43  358.36  358.35  358.09  357.99  357.76  357.50  357.27  357.28  360.56
  364.51  364.98
 -642.05 -642.04 -641.98 -641.94 -641.94 -641.91 -641.91 -641.86 -641.80 -641.79
 -641.71 -641.59 -641.59 -641.56 -641.44 -641.43 -641.37 -641.32 -641.30 -641.26
 -641.24 -641.19 -641.20  354.30  354.28 -641.22 -641.23 -641.25 -641.36 -641.51
 -641.57 -641.64 -641.65 -641.91 -642.01 -642.24 -642.50 -642.73 -642.72 -639.44
 -635.49 -635.02
 9805.24 9807.67 9812.14 9818.66 9829.65 9836.25 9840.64 9851.63 9860.37 9862.62
 9873.61 9884.48 9884.59 9895.58 9906.57 9908.59 9917.56 9928.55 9932.70 9939.54
 9943.84 9950.30 9977.92 9977.9210047.9210047.9210064.4110067.6710073.6310084.81
10090.0310095.3910095.9910107.0710113.0210118.1610129.2410136.1910140.3310151.41
10159.3710161.01
  357.95  357.96  358.02  358.06  358.06  358.09  358.09  358.14  358.20  358.21
  358.29  358.41  358.41  358.44  358.56  358.57  358.63  358.68  358.70  358.74
  358.76  358.81  358.80  358.80  358.78  358.78  358.77  358.75  358.64  358.49
  358.43  358.36  358.35  358.09  357.99  357.76  357.50  357.27  357.28  360.56
  364.51  364.98
 -642.05 -642.04 -641.98 -641.94 -641.94 -641.91 -641.91 -641.86 -641.80 -641.79
 -641.71 -641.59 -641.59 -641.56 -641.44 -641.43 -641.37 -641.32 -641.30 -641.26
 -641.24 -641.19 -641.20  354.30  354.28 -641.22 -641.23 -641.25 -641.36 -641.51
 -641.57 -641.64 -641.65 -641.91 -642.01 -642.24 -642.50 -642.73 -642.72 -639.44
 -635.49 -635.02
BR Coef=-1 , 0 , 0 ,, 0 ,,,0.8,0,1,0,
WSPro=,,,, 1 ,,,, 0 ,,,, 0 ,,,,-1 ,-1 ,-1 , 0 , 0 , 0 , 0 , 0
BC Design=,, 0 ,, 0 ,,,,,,

Type RM Length L Ch R = 1 , 8099.18,238.636300,238.636300,238.636300
XS GIS Cut Line= 6
788109.303672075 784132.15612784788131.914902419783985.496291608
788132.263186306783862.839258879788087.390378624783612.710908055
787954.240571648783417.599982947 787771.37916261783005.596186399
#Sta/Elev= 30
9121.141441.28569158.977431.29149198.929423.26289250.018 401.3559300.161386.0593
9350.192376.01979360.197369.82959370.203366.92369552.008359.65339582.846361.8181
9623.964355.46429704.638353.33969740.958354.99239765.171359.88719801.491357.4213
9952.273358.73319963.324358.29779975.268351.53719996.476345.032710029.63348.2064
10062.52357.235310106.19356.1863 10171.7   358.410193.47366.891210215.17381.3525
10236.88389.610210247.73391.616410269.44390.741710291.15394.589810333.92394.1114
#Mann= 3 , 0 , 0
9121.141  0.0715       09121.141  0.0715       010333.92  0.0715       0
#XS Ineff= 2 , 0
       09942.729        10079.42       0
Bank Sta=9121.141,10333.92
Exp/Cntr=0.3,0.1

Type RM Length L Ch R = 1 ,7860.544,477.272500,477.272500,477.272500
XS GIS Cut Line= 6
788218.225362859783974.633781955788254.283910521783801.256001652
788248.711600119783580.362300788788205.059256061783409.436260611
788040.272228409783006.798202491787968.420055093782602.176059335
#Sta/Elev= 30
9237.268426.81619299.111399.08759339.981  367.669360.366361.14539410.843361.3207
9420.895356.26299491.021351.15089571.125354.1731 9641.61350.05619661.971354.3623
9702.745349.01339785.944350.48479806.952356.72159838.976358.61999936.776359.3143
9970.193352.47899992.471343.941510025.74345.936110036.81351.152610058.95353.6708
   10198351.156610399.68358.611710435.22366.005510455.53373.813410485.94378.3911
10516.35381.153510526.43 374.44410536.51372.961210607.07387.833210660.09390.2972
#Mann= 3 , 0 , 0
9237.268  0.0693       09237.268  0.0693       010660.09  0.0693       0
#XS Ineff= 2 , 0
       09908.659        10107.99       0
Bank Sta=9237.268,10660.09
Exp/Cntr=0.3,0.1

Type RM Length L Ch R = 1 ,7383.272,477.272600,477.272600,477.272600
XS GIS Cut Line= 6
  788273.1535978783974.633781955788391.011983526783687.138999101
788479.130906297783355.717516573788559.456006747783129.033771272
 788611.63081095782896.194671419788700.683185666782618.244491475
#Sta/Elev= 30
9044.966435.90319155.691369.00979188.312357.64259231.592349.90069295.466347.0655
9431.036346.09669462.002349.71049523.933347.35519544.577349.83099554.899348.0791
9575.542350.31519585.864348.60279647.885350.97459668.689348.19729933.411348.5298
10005.13340.142710015.21 340.31910025.33347.559910045.81 357.08210107.42376.4146
10169.48383.0576 10242.4383.270210273.68380.976910305.14374.808210336.64361.1798
10347.14359.834810389.31361.699810410.47366.6338 10442.2 363.863 10470.5365.6711
#Mann= 3 , 0 , 0
9044.966  0.0474       09044.966  0.0474       0 10470.5  0.0474       0
#XS Ineff= 2 , 0
       0 9656.76                       0
Bank Sta=9044.966,10470.5
Exp/Cntr=0.3,0.1

Type RM Length L Ch R = 1 ,6905.999,238.636300,238.636300,238.636300
XS GIS Cut Line= 6
788337.291441776783974.633781955788419.844247631 783885.72741739
788626.671047898783697.056921587788707.569679538783615.324053267
789037.982380244783210.390177134 789315.41539228782416.984566525
#Sta/Elev= 30
9234.808423.95419246.418417.55479261.479403.96019274.439394.87049301.555388.8296
9315.458383.79719343.266362.64129376.966349.77749653.423343.13239777.996344.1114
 9808.79342.69769967.228  345.129984.695339.72379997.515338.048910015.18342.1824
10087.15345.043210111.26 342.80110176.86345.123810385.48345.275510449.04348.4834
10470.23346.642610576.17349.417810597.35353.329210607.95349.816110650.32349.9626
10671.51352.523310703.29352.187510798.63 357.26710904.57 365.28611114.34372.7982
#Mann= 3 , 0 , 0
9234.808  0.0494       09234.808  0.0494       011114.34  0.0494       0
#XS Ineff= 2 , 0
       09816.482         10152.2       0
Bank Sta=9234.808,11114.34
Exp/Cntr=0.3,0.1

Type RM Length L Ch R = 1 ,6667.363,477.272500,477.272500,477.272500
XS GIS Cut Line= 6
788376.046553306783974.633781955788555.753930474783856.050705089
789030.805935756783637.774981521789115.362887793783425.343626225
 789246.86474058783268.371240124789644.614507467782581.275455698
#Sta/Elev= 30
9140.446419.19689164.705399.98079204.599382.81849227.657370.08719287.107352.8057
9298.681358.94229310.034358.5038 9332.74350.64299358.819354.97529421.363346.6052
9623.612341.93559644.818 339.8529932.985342.48579974.884345.98759985.165 344.801
9995.447336.897310026.49  340.3710069.36339.5571 10091.7346.1247 10176.1346.9283
10243.03344.853510283.19348.652310530.72349.2701 10674.4352.929110888.91354.1324
10933.88352.6399 10969.8360.927411027.57361.596911062.23368.480811112.76370.8056
#Mann= 3 , 0 , 0
9140.446  0.0491       09140.446  0.0491       011112.76  0.0491       0
#XS Ineff= 2 , 0
       09693.998        10126.78       0
Bank Sta=9140.446,11112.76
Exp/Cntr=0.3,0.1

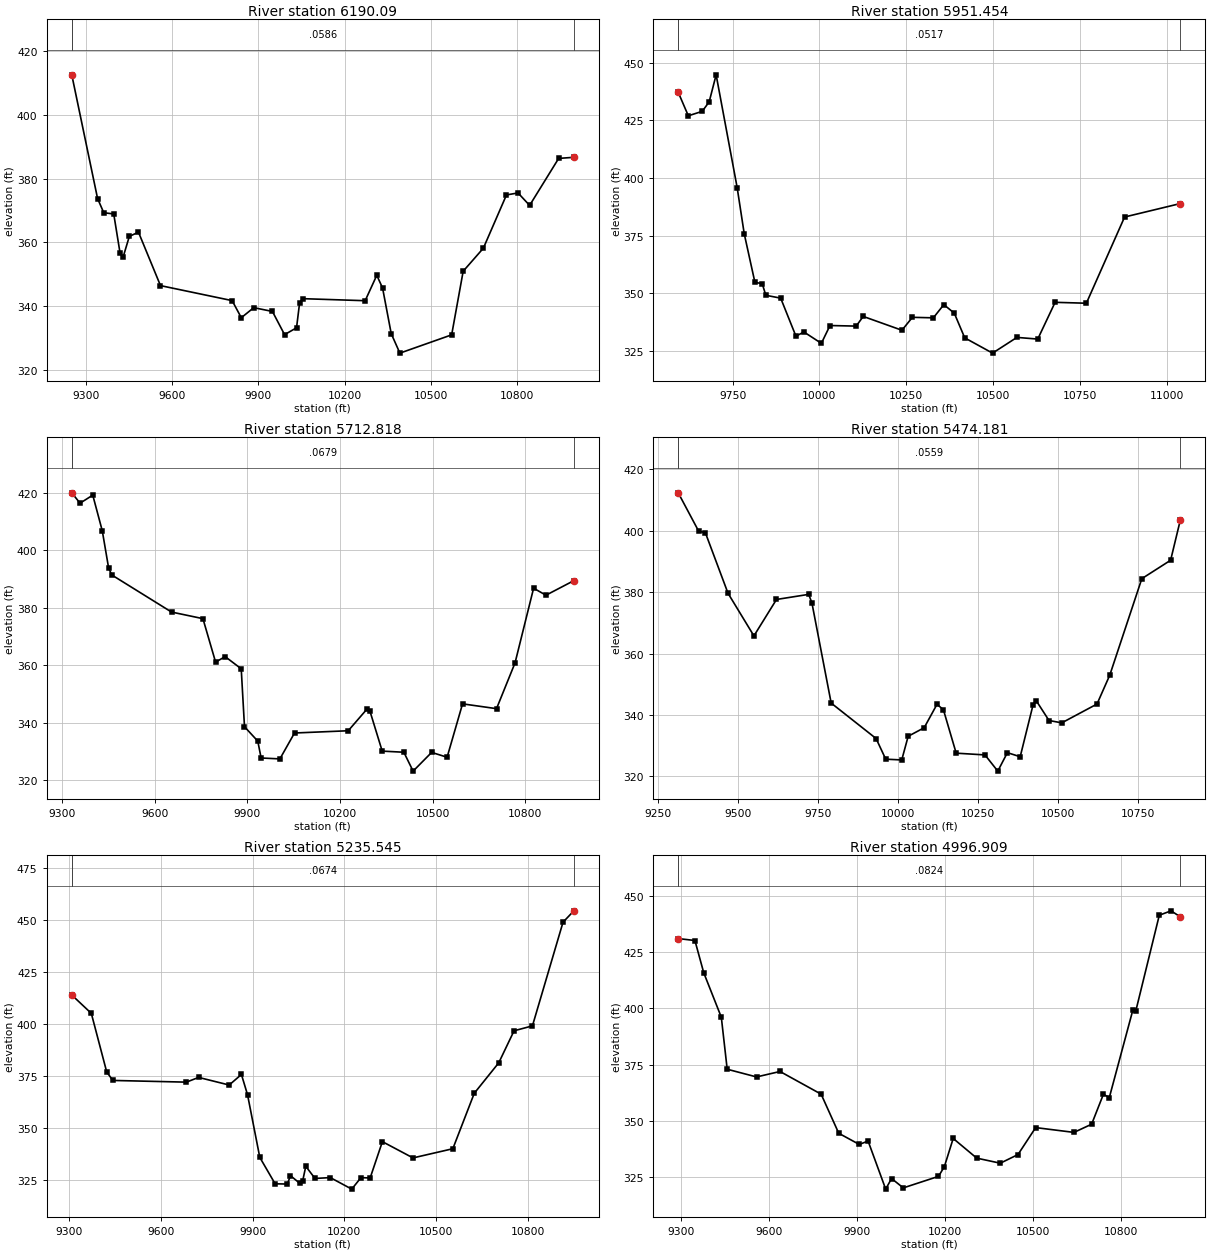
Type RM Length L Ch R = 1 , 6190.09,238.636300,238.636300,238.636300
XS GIS Cut Line= 6
788400.003992517783974.633781955 788590.03243667783873.176402568
788787.248764813783836.461373803789418.838191891784004.469968479
789698.883516187784009.610526556790087.099909833783964.691549055
#Sta/Elev= 30
9251.451412.61889341.202373.76939362.715369.31629397.414 368.9319419.454356.6128
9430.183355.42729451.641361.88999483.436363.20669559.979346.42639809.127341.7174
 9841.01 336.3489884.357339.5007 9949.23338.31999991.494331.035810033.13333.1792
10043.64340.895910054.17342.331110271.82341.688710312.21349.668310332.36 345.674
10362.45331.340810392.54325.227110572.64330.969710612.67350.947410682.85358.1779
10763.22374.900510803.45375.529510843.77371.616510944.73386.374110997.55386.7174
#Mann= 3 , 0 , 0
9251.451  0.0586       09251.451  0.0586       010997.55  0.0586       0
#XS Ineff= 2 , 0
       09814.717           10653       0
Bank Sta=9251.451,10997.55
Exp/Cntr=0.3,0.1

Type RM Length L Ch R = 1 ,5951.454,238.636300,238.636300,238.636300
XS GIS Cut Line= 6
788586.090431239784024.520270235 788806.83668577 784041.13085248
789027.119528729784154.985352077789202.035478602784188.321670869
789551.899760266784213.626538208789995.050937493784198.354324997
#Sta/Elev= 30
9593.405437.1626 9622.46426.98849662.506428.92539682.511433.04559702.517444.7396
9763.076395.88379783.427375.8848 9814.27354.77749835.128354.32589845.572349.2282
9888.404347.98569932.298331.51299955.391333.320710005.53328.402210030.39336.1233
10105.71335.871210126.15340.062310237.52334.074310267.71339.675310328.02339.4576
10358.17345.175710388.29341.483510418.36  330.7810498.54324.1627 10568.6330.9753
10628.62330.251110678.62346.173910768.63345.782410878.72383.138511039.15388.9647
#Mann= 3 , 0 , 0
9593.405  0.0517       09593.405  0.0517       011039.15  0.0517       0
#XS Ineff= 2 , 0
       0                10691.57       0
Bank Sta=9593.405,11039.15
Exp/Cntr=0.3,0.1

Type RM Length L Ch R = 1 ,5712.818,238.636200,238.636200,238.636200
XS GIS Cut Line= 6
788379.328095094784504.639112802788907.489669809784390.527901855
788975.243619428784364.377537651789076.778225185784299.781329829
789136.092080831784283.412924438789965.125962332784274.317723484
#Sta/Elev= 30
9331.724420.06929358.531416.46479399.708419.26419430.537406.83379451.089393.8705
9461.365391.47619654.691378.57219756.395376.27259797.404361.13469828.325363.0585
9880.371358.82169890.953338.6562 9933.93333.65179944.836327.772310005.59 327.456
10052.88336.469410226.84337.254110286.84344.709810296.84344.189810336.86330.1635
10406.89329.775610436.91323.199310496.94329.721110546.96328.031310596.96 346.616
10706.97344.941910766.98360.893510827.01386.869810867.05384.433210957.32389.4992
#Mann= 3 , 0 , 0
9331.724  0.0679       09331.724  0.0679       010957.32  0.0679       0
#XS Ineff= 2 , 0
       0                10607.12       0
Bank Sta=9331.724,10957.32
Exp/Cntr=0.3,0.1

Type RM Length L Ch R = 1 ,5474.181,238.636300,238.636300,238.636300
XS GIS Cut Line= 6
788362.434648187784649.677227233788460.613670247784628.213662991
788604.208123107784605.856163869788872.563876806784578.259939365
789083.912334995784564.318705399789925.307492629784574.154593777
#Sta/Elev= 30
9314.081412.32129378.262399.76539398.667399.39419469.638379.62279550.602365.7442
 9621.12377.60359721.727 379.2639731.767376.50399792.003343.87059932.376332.3269
9962.442325.607810012.55325.360510032.59333.064610082.61335.844110122.61 343.455
10142.61341.750210182.62327.566710272.64326.995210312.65321.719410342.65327.7323
10382.66326.403210422.67343.209610432.67344.670510472.68338.199610512.69337.4367
10622.72343.563810662.73 353.00510762.73 384.37510852.73390.371610883.03 403.444
#Mann= 3 , 0 , 0
9314.081  0.0559       09314.081  0.0559       010883.03  0.0559       0
#XS Ineff= 2 , 0
       0                10439.63       0
Bank Sta=9314.081,10883.03
Exp/Cntr=0.3,0.1

Type RM Length L Ch R = 1 ,5235.545,238.636300,238.636300,238.636300
XS GIS Cut Line= 6
788341.826421254784826.608459364788547.926519274784802.505198912
 788825.89507454784794.338392978788925.572471721784797.229599383
789609.276394203784841.728608256789980.377980518784857.102962604
#Sta/Elev= 30
9308.445413.97319372.355405.16259422.724377.01969442.806372.95149683.277372.1346
9723.278374.40379823.292370.75079863.309375.82369883.317366.07069923.393336.0069
9973.515323.321510013.62323.208710023.65327.253410053.74323.598310063.77324.8158
 10073.8331.728410103.89325.889310154.03326.305610224.15320.766110254.21326.2937
10284.26326.116710324.33343.559910424.51335.753210554.74 340.16510624.84366.7922
10704.94381.4239   10755396.796310815.06399.144210915.11448.9237 10950.5454.3883
#Mann= 3 , 0 , 0
9308.445  0.0674       09308.445  0.0674       0 10950.5  0.0674       0
#XS Ineff= 2 , 0
       0                10335.57       0
Bank Sta=9308.445,10950.5
Exp/Cntr=0.3,0.1

Type RM Length L Ch R = 1 ,4996.909,238.636300,238.636300,238.636300
XS GIS Cut Line= 6
788318.194907511785029.496017625 788493.94733007785024.733587736
 788897.62199793785042.776601302789218.536161844 785045.08914078
789828.323783989  785100.6157513790026.510869956 785113.80906467
#Sta/Elev= 30
9291.869431.02479348.757430.16169378.769415.86589438.773396.08979458.774373.0103
9558.819369.5834 9638.89372.00919779.074361.93549839.154 344.5739909.197339.6139
9939.197341.12569999.197319.7717 10019.2324.4902 10059.2 320.32110179.24325.4371
10199.27 329.75610229.35342.267610309.59333.534710389.95 331.28410450.24335.1164
10510.54347.093510641.16 344.96310701.39 348.60110741.55361.905310761.63360.4101
10841.88 399.275 10851.9398.837610932.08441.396710972.16443.345211003.74440.6822
#Mann= 3 , 0 , 0
9291.869  0.0824       09291.869  0.0824       011003.74  0.0824       0
#XS Ineff= 2 , 0
       0                10244.92       0
Bank Sta=9291.869,11003.74
Exp/Cntr=0.3,0.1

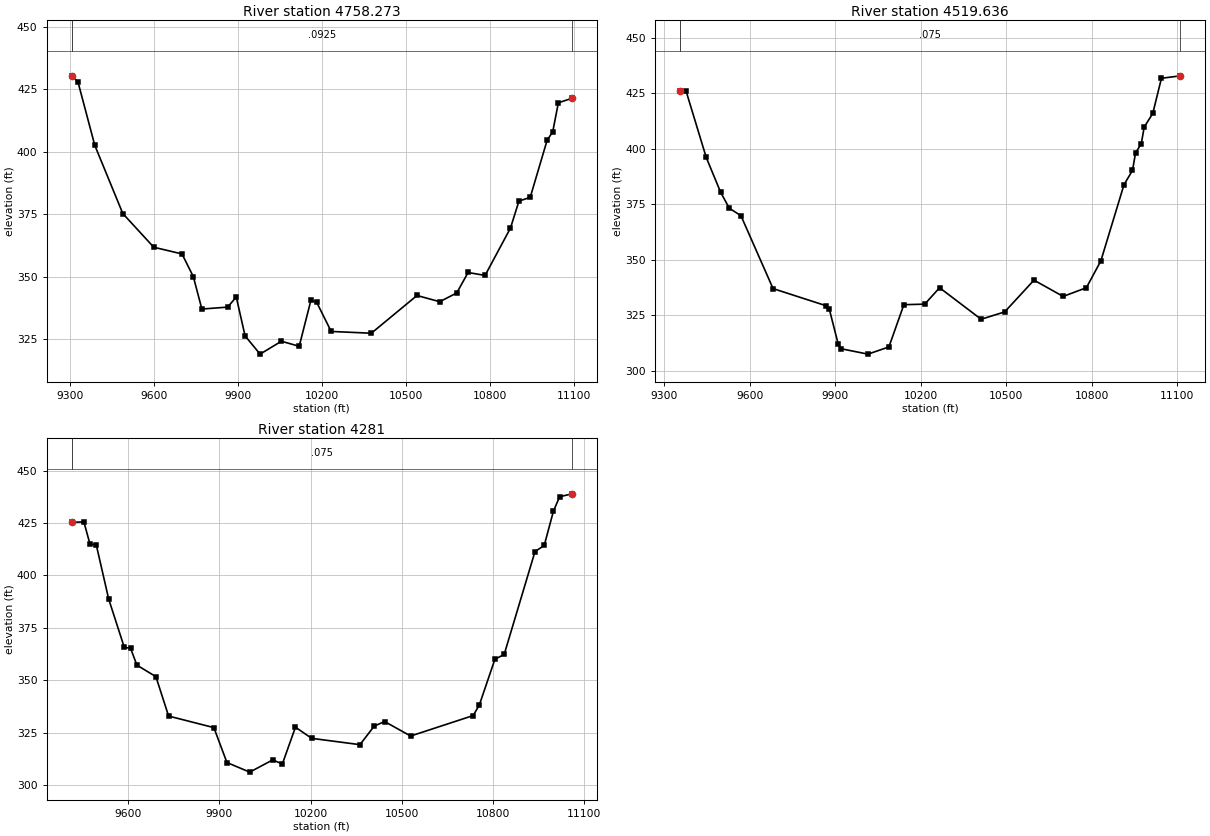
Type RM Length L Ch R = 1 ,4758.273,238.636200,238.636200,238.636200
XS GIS Cut Line= 6
788312.545777749785158.517865166788567.486111415785173.475977257
788799.038995213785208.550771701789300.755182092 785361.84163294
789665.148884184785431.635101105790063.566328408785481.513229242
#Sta/Elev= 30
9304.438 430.3159326.893427.89319386.935402.57769487.133375.30749597.755361.8462
9698.764359.16649739.283350.07339769.767337.15599861.708337.91569892.755 341.947
 9924.17326.43529977.836319.1441   10054324.291410117.65322.277710159.45340.6412
10180.19339.843210231.84328.200810375.48327.494710538.66342.565410619.95340.0766
 10680.8343.592410721.28351.754710781.95350.576510872.78369.510410903.02380.2701
10943.34381.770911003.71404.556111023.81407.9686 11043.9419.550811092.71421.3441
#Mann= 3 , 0 , 0
9304.438  0.0925       09304.438  0.0925       011092.71  0.0925       0
#XS Ineff= 2 , 0
       0                10169.53       0
Bank Sta=9304.438,11092.71
Exp/Cntr=0.3,0.1

Type RM Length L Ch R = 1 ,4519.636,238.636300,238.636300,238.636300
XS GIS Cut Line= 6
788303.976536464785354.232849268788415.287828691785367.664352661
788668.361754404785420.582887966789487.869828152785657.157717151
789794.519466008785717.323718913790011.020960862785747.034261784
#Sta/Elev= 30
9355.618426.20799376.792426.02489447.302396.19929497.943380.4904 9528.44373.2851
9569.103369.9442 9681.81337.10059868.266329.36519878.651328.08699909.866312.3386
9920.351310.007310014.72307.585910088.15310.817910140.61329.853510213.83330.0996
10265.95 337.49210411.58323.2988 10494.3326.611710597.07340.909210699.29333.5786
10780.87337.501210831.65349.601110912.82383.916810942.55390.329910953.29398.1666
10973.52402.4376 10983.6409.831811013.84416.055211044.09431.835411110.64432.9456
#Mann= 3 , 0 , 0
9355.618   0.075       09355.618   0.075       011110.64   0.075       0
#XS Ineff= 2 , 0
       0                10157.95       0
Bank Sta=9355.618,11110.64
Exp/Cntr=0.3,0.1

Type RM Length L Ch R = 1 ,    4281,0.000000,0.000000,0.000000
XS GIS Cut Line= 6
788295.296037304785552.488878991788599.346576947785626.669729395
789133.280057925785830.191852692789298.702133103785883.023942477
789622.933200655785962.759864437789875.404386528786005.938630955
#Sta/Elev= 30
9413.015 425.2889453.208425.55239473.503414.81679493.919414.65639534.902388.7091
 9586.35365.6496 9607.03365.20779627.903357.17439690.523351.66929732.376332.8598
9881.539327.34619924.533310.67989999.775306.098610075.06311.904810107.32310.0296
10150.34327.559610203.79322.222710362.86319.205210409.64328.006310443.96330.2593
10529.95323.330210735.94333.098410756.42338.199510807.59359.982410838.14362.2496
10939.69411.379610970.09414.2808 11000.5430.677911020.77437.533411061.65438.9265
#Mann= 3 , 0 , 0
9413.015   0.075       09413.015   0.075       011061.65   0.075       0
#XS Ineff= 2 , 0
       0                10162.03       0
Bank Sta=9413.015,11061.65
Exp/Cntr=0.3,0.1